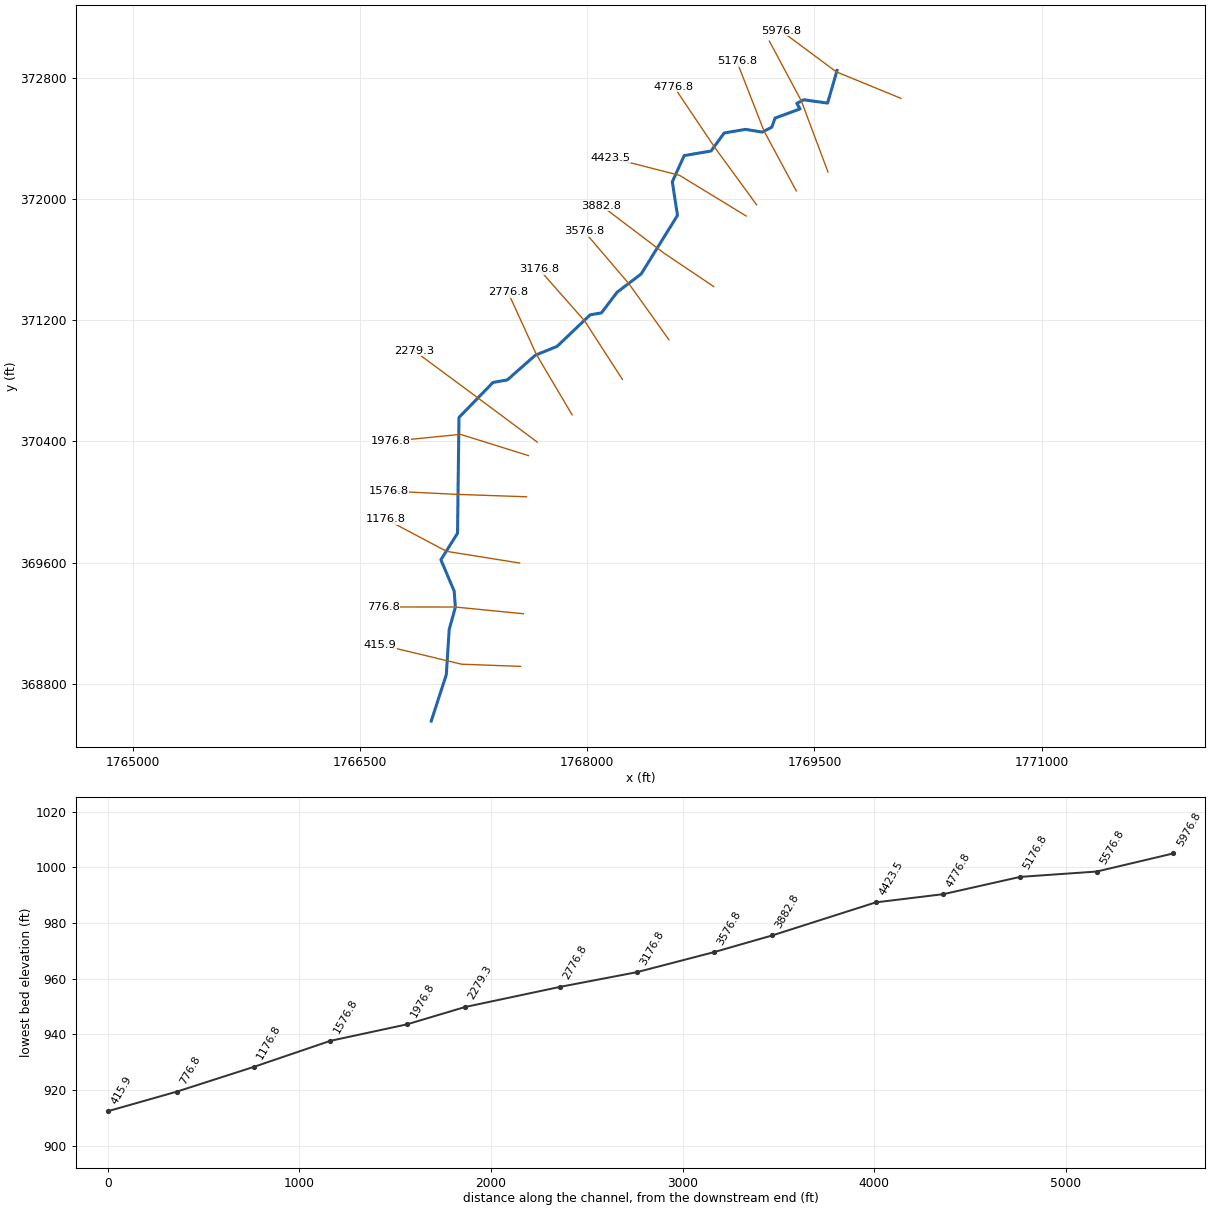
--- DvyRn.prj (project) ---

Proj Title=DvyRn
Current Plan=p01
Default Exp/Contr=0,0
English Units
Geom File=g01
Flow File=f01
Plan File=p01
BEGIN DESCRIPTION:
END DESCRIPTION:
DSS Export Rating Curves= 0
DSS Export Rating Curve Sorted= 0
DSS Export Volume Flow Curves= 0
DXF OffsetX= 0
DXF OffsetY= 0
DXF ScaleX= 0
DXF ScaleY= 0

--- DvyRn.p01 (plan) ---

Plan Title=Floodplain
Program Version=4.00
Geom File=g01
Flow File=f01
K Sum by GR=0
Std Step Tol=0.01
Critical Tol=0.01
Num of Std Step Trials=20
Max Error Tol=0.3
Flow Tol Ratio=0.001
Split Flow NTrial=30
Split Flow Tol=0.02
Split Flow Ratio=0.02
Log Output Level=0
Friction Slope Method=1
Unsteady Friction Slope Method=2
Unsteady Bridges Friction Slope Method=1
Global Log Level=0
CheckData=False
Run HTab=0
Run UNet=0
Run PostProcess=0
UNET Theta=0
UNET Theta Warmup=0
UNET ZTol=0
UNET ZSATol=0
UNET MxIter=0
UNET MaxInSteps=0
UNET DtIC=0
UNET DtMin=0
UNET MaxCRTS=0
UNET WFStab=0
UNET SFStab=0
UNET WFX=0
UNET SFX=0
UNET DSS MLevel=0
UNET DZMax Abort=0
UNET Convert EG Bridges=0
UNET Use Existing IB Tables=0
UNET Froude Limit=0
UNET Froude Power=0
Write IC File=0
Echo Input=False
Echo Output=False
Write Detailed=0

--- DvyRn.f01 (steady flow) ---

Flow Title=NFF Regression Equation
Program Version=4.00
Number of Profiles= 1
Profile Names=P100yr
River Rch & RM=DvyRn,Main            ,5976.8
  726.28
River Rch & RM=DvyRn,Main            ,5576.8
772.2763
River Rch & RM=DvyRn,Main            ,4423.5
889.1939
River Rch & RM=DvyRn,Main            ,3882.8
 907.661
River Rch & RM=DvyRn,Main            ,3176.8
  999.85
Boundary for River Rch & Prof#=DvyRn,Main            , 1
Up Type= 0
Dn Type= 3
Dn Slope=0.01655
DSS Import GetInterval= 0
DSS Import GetPeak= 0
DSS Import FillOption= 0

--- DvyRn.g01 (geometry) ---

Geom Title=USGS 3m DEM
Program Version=4.00

River Reach=DvyRn           ,Main
Reach XY= 30
     1769649.052      372848.917     1769586.622      372633.431
     1769429.538      372655.584     1769383.219      372631.417
     1769405.372      372595.168     1769240.233      372534.751
      1769218.08      372474.334      1769155.65      372442.112
     1769044.887      372460.237     1768903.915      372436.071
     1768817.318      372317.251     1768640.096      372287.043
     1768561.554      372113.849      1768595.79      371892.322
     1768356.138      371505.656     1768197.041      371384.823
     1768093.618      371248.488      1768019.17      371235.643
     1767800.726      371027.443     1767657.103      370969.045
     1767472.307      370806.011     1767377.632      370789.298
     1767153.178      370557.947     1767143.606      369793.716
     1767033.716       369618.61     1767121.376      369412.625
     1767129.365      369304.971     1767088.609      369157.953
     1767069.591       368859.88      1766969.98      368553.564

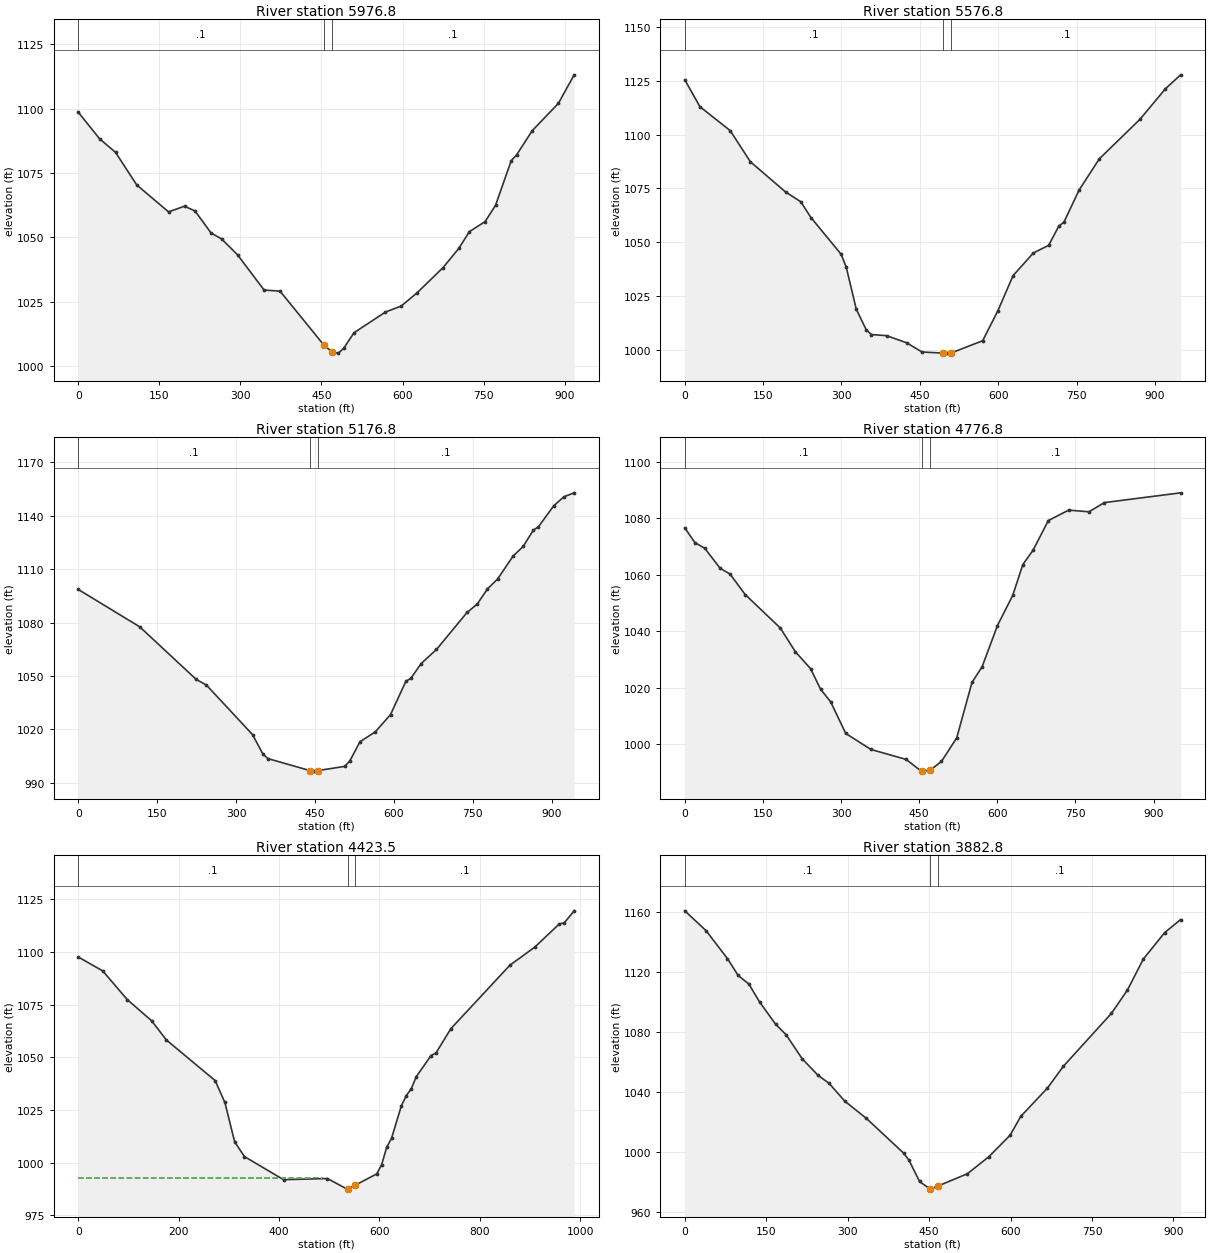
Type RM Length L Ch R = 1 ,5976.8  ,434.711,400,383.903
XS GIS Cut Line= 3
     1770070.939      372664.894     1769643.826      372840.391
     1769277.759      373112.163
#Sta/Elev= 30
       0 1098.66    39.3 1088.35    68.8 1083.09   108.1  1070.4     167 1059.93
   196.5 1062.15   216.1 1060.27   245.6 1051.75   265.3 1049.39   294.7 1043.23
   343.9 1029.53   373.3 1029.13   454.3  1008.2   469.3 1005.55   481.2 1005.02
   490.9 1006.83   510.3 1012.96   568.5    1021   597.6 1023.31   626.7 1028.41
   675.2  1038.3   704.3 1045.77   723.7 1052.23   752.8 1056.14   772.2 1062.48
   801.3 1079.87     811 1082.03   840.1  1091.5   888.6 1102.14   917.7 1113.21
#Mann= 3 , 0 , 0
       0      .1       0   454.3    .045       0   469.3      .1       0
Bank Sta=454.3,469.3
XS Rating Curve= 0 ,0
Exp/Cntr=0.3,0.1

Type RM Length L Ch R = 1 ,5576.8  ,357.849,400,399.387
XS GIS Cut Line= 3
      1769589.48      372178.415     1769413.014      372648.699
      1769202.29      373042.936
#Sta/Elev= 30
       0 1125.46      29 1112.96    86.9 1101.88   125.6 1087.39   193.2 1073.32
   222.2 1068.81   241.5 1061.48   299.4 1044.42   309.1 1038.42   328.4 1018.88
   347.7 1009.18   357.4 1007.14   386.4 1006.62     425 1003.29     454  999.04
   494.8  998.52   502.3  998.51   509.8  998.58   570.3 1004.27   599.5 1018.26
   628.6 1034.55   667.5 1045.06   696.7 1048.59   716.1 1057.54   725.8  1059.3
     755  1074.3   793.8  1088.8   871.6 1107.15   920.2 1121.31   949.3 1127.78
#Mann= 3 , 0 , 0
       0      .1       0   494.8    .045       0   509.8      .1       0
Bank Sta=494.8,509.8
XS Rating Curve= 0 ,0
Exp/Cntr=0.3,0.1

Type RM Length L Ch R = 1 ,5176.8  ,397.364,400,404.147
XS GIS Cut Line= 3
     1769379.955      372053.999     1769167.529      372448.509
     1768987.476      372908.845
#Sta/Elev= 30
       0 1098.55   116.9 1077.54     224 1048.08   243.5 1044.89   331.2 1017.05
   350.7 1006.22   360.4 1003.61   440.6  996.85   448.1  996.58   455.6   996.9
   506.2  999.24   515.9 1002.25   535.3 1013.05   564.4 1018.61   593.4 1028.34
   622.5 1046.98   632.2 1048.75   651.6 1056.99   680.7 1064.87   738.8 1085.64
   758.2 1090.35   777.6 1098.86     797 1104.46   826.1 1117.21   845.4  1122.7
   864.8 1131.82   874.5 1133.76   903.6 1145.54     923 1150.62   942.4 1152.81
#Mann= 3 , 0 , 0
       0      .1       0   440.6    .045       0   455.6      .1       0
Bank Sta=440.6,455.6
XS Rating Curve= 0 ,0
Exp/Cntr=0.3,0.1

Type RM Length L Ch R = 1 ,4776.8  ,335.703,353.283,371.251
XS GIS Cut Line= 3
     1769118.253      371962.219     1768844.851      372336.525
     1768572.212      372741.832
#Sta/Elev= 30
       0 1076.65    19.3 1071.46    38.6 1069.38    67.6 1062.37    86.9 1060.27
   115.9 1053.02   183.5 1041.13   212.4 1032.69   241.4 1026.75   260.7 1019.44
     280 1014.98     309 1003.75   357.3  998.07   424.9  994.54   453.9  990.38
     456  990.41     471  990.71   492.8  993.81   522.1 1002.18   551.4 1021.83
     571 1027.46   600.3 1042.02   629.6  1052.7   649.1 1063.66   668.7 1068.75
     698 1079.26   737.1 1082.96   776.1 1082.36   805.5 1085.62     952 1089.09
#Mann= 3 , 0 , 0
       0      .1       0     456    .045       0     471      .1       0
Bank Sta=456,471
XS Rating Curve= 0 ,0
Exp/Cntr=0.3,0.1

Type RM Length L Ch R = 1 ,4423.5  ,549.606,540.68,531.755
XS GIS Cut Line= 3
     1769049.512      371888.077     1768608.973      372156.964
     1768151.449      372273.696
#Sta/Elev= 30
       0 1097.58    48.7 1090.99    97.4 1077.41   146.1 1067.33   175.3 1058.26
   272.7 1038.94   292.1 1028.54   311.6 1009.86   331.1 1002.88     409  991.91
   496.6  992.45   535.8  987.42   536.7  987.51   551.7  989.23   594.8  994.67
   604.6  999.04   614.5 1007.18   624.3 1011.57     644 1027.04   653.8 1031.84
   663.7 1035.06   673.5 1040.75     703 1050.82   712.9 1052.04   742.4 1063.53
   860.4 1093.75   909.6 1102.24   958.8 1113.33   968.6  1113.8   988.3 1119.51
#Mann= 3 , 0 , 0
       0      .1       0   536.7    .045       0   551.7      .1       0
#XS Ineff= 2 , 0
          486.36  992.48
Permanent Ineff=
       F       F
Bank Sta=536.7,551.7
XS Rating Curve= 0 ,0
Exp/Cntr=0.3,0.1

Type RM Length L Ch R = 1 ,3882.8  ,312.962,306.036,301.064
XS GIS Cut Line= 3
      1768835.03      371422.318     1768508.776      371641.665
     1768094.191      371955.896
#Sta/Elev= 30
       0  1161.1    39.3 1147.84    78.6 1129.23    98.3    1118   117.9 1112.33
   137.6 1100.41   167.1 1085.58   186.7 1078.43   216.2 1062.47   245.7 1051.32
   265.4  1046.2   294.9 1034.13   334.2  1022.8   402.9  999.59   412.8   994.9
   432.4  980.64   451.8  975.56     452  975.53   466.8  977.67   520.7  985.83
     560  997.13   599.3 1011.52   618.9 1024.06     668  1042.9   697.4 1057.49
   785.7 1092.66   815.2  1108.2   844.6 1128.93   883.9 1146.57   913.3 1155.27
#Mann= 3 , 0 , 0
       0      .1       0   451.8    .045       0   466.8      .1       0
Bank Sta=451.8,466.8
XS Rating Curve= 0 ,0
Exp/Cntr=0.3,0.1

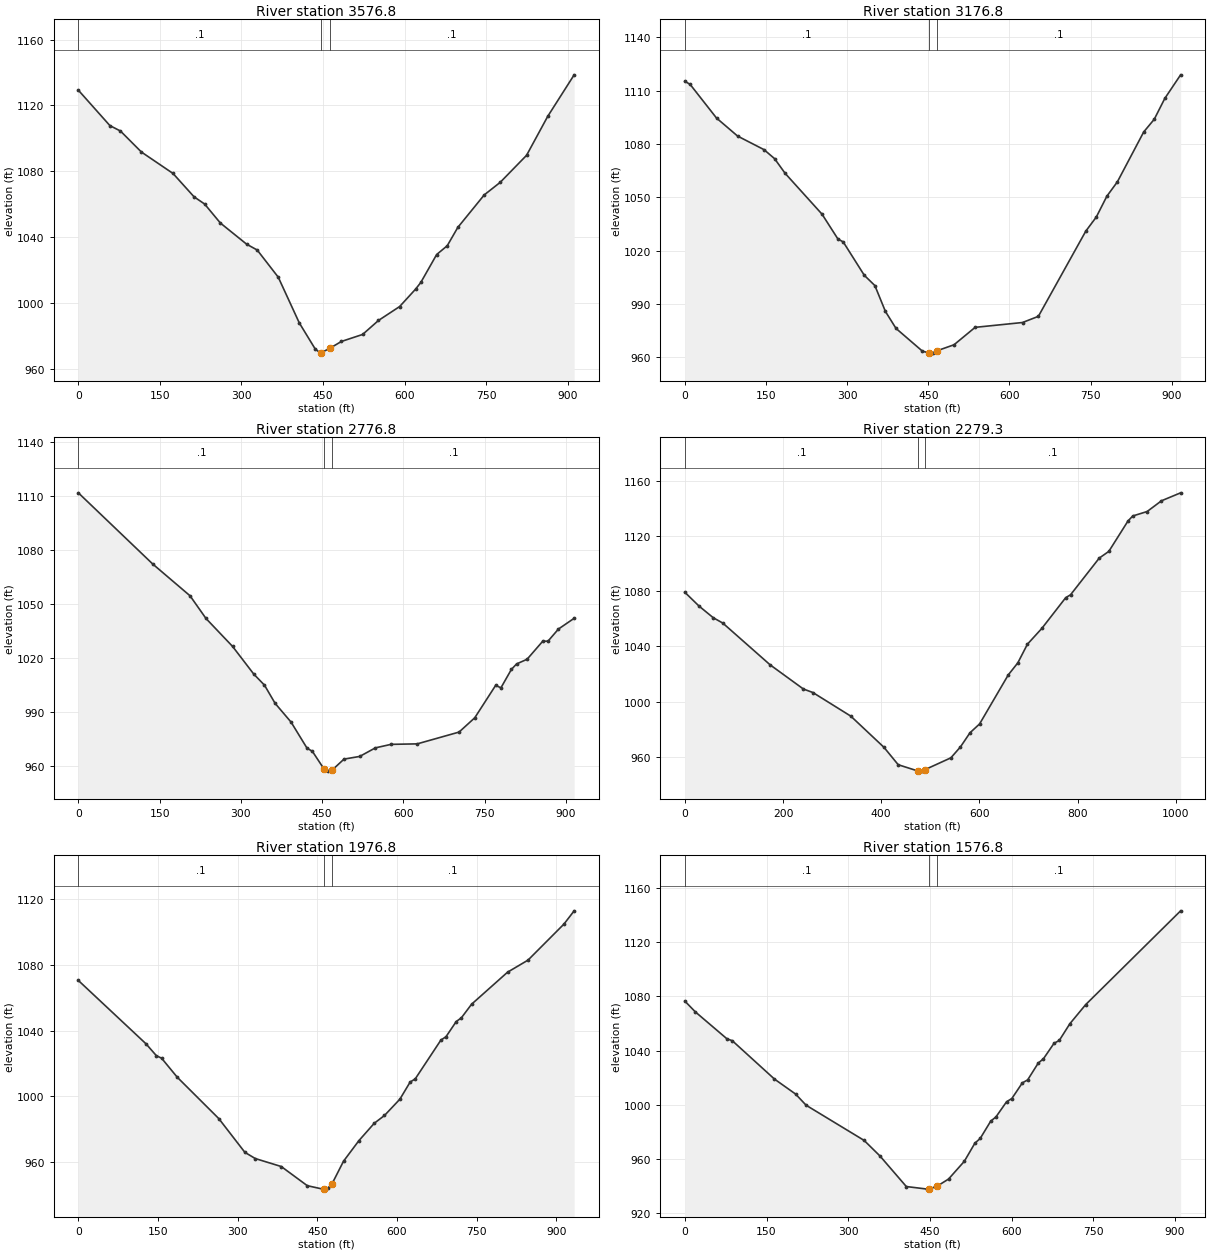
Type RM Length L Ch R = 1 ,3576.8  ,401.022,400,400.525
XS GIS Cut Line= 3
      1768539.65      371070.843       1768275.4      371440.793
     1767978.551      371788.359
#Sta/Elev= 30
       0 1129.26      58 1107.73    77.4 1104.44   116.1 1091.64   174.1 1078.65
   212.8 1064.45   232.2 1060.08   261.2 1048.52   309.5 1035.67   328.9 1032.13
   367.6 1015.63   406.3  987.84   435.3  972.14     445  969.49   447.1  969.84
   462.1  972.37   483.8  976.59   522.7  980.83   551.9  989.34   590.8  997.79
     620 1008.33   629.7 1012.41   658.9  1029.4   678.3 1034.72   697.8 1045.88
   746.4 1065.63   775.6 1073.21   824.2 1089.67   863.1 1113.34   911.7 1138.57
#Mann= 3 , 0 , 0
       0      .1       0   447.1    .045       0   462.1      .1       0
Bank Sta=447.1,462.1
XS Rating Curve= 0 ,0
Exp/Cntr=0.3,0.1

Type RM Length L Ch R = 1 ,3176.8  ,401.197,400,392.899
XS GIS Cut Line= 3
     1768231.713      370809.914     1767983.097      371195.368
     1767680.265      371538.615
#Sta/Elev= 30
       0 1115.25     9.8  1113.5    58.6 1094.56    97.6 1084.41   146.4 1076.78
   165.9 1071.72   185.4 1063.47   253.7 1040.46     283 1026.53   292.8 1024.88
   331.8 1006.09   351.3 1000.33   370.8  985.77   390.4  976.22   439.2  963.43
   451.2  962.48   458.7  962.33   466.2  963.66   497.6  967.03   536.6  976.83
   624.2  979.55   653.5  983.02   741.1 1030.93   760.6  1038.9   780.1  1050.6
   799.5 1058.67   848.2 1086.74   867.7 1093.89   887.2 1105.61   916.4 1118.86
#Mann= 3 , 0 , 0
       0      .1       0   451.2    .045       0   466.2      .1       0
Bank Sta=451.2,466.2
XS Rating Curve= 0 ,0
Exp/Cntr=0.3,0.1

Type RM Length L Ch R = 1 ,2776.8  ,488.557,497.446,508.712
XS GIS Cut Line= 3
     1767900.235      370575.571     1767664.985      370972.626
     1767476.434      371385.458
#Sta/Elev= 30
       0 1111.52   137.5 1071.97   206.2 1054.38   235.7 1041.78   284.8 1026.26
     324 1010.88   343.7 1004.76   363.3  994.68   392.8  984.25   422.2  969.81
   432.1  968.05     454  958.05   461.5  957.06     469  957.76   490.5  963.73
   519.5  965.22   548.4  969.97   577.4  971.92   625.7  972.19   702.9  978.73
   731.9  986.67   770.5 1004.67   780.2  1003.3   799.5  1013.5   809.1 1016.55
   828.5 1019.15   857.4 1029.16   867.1 1029.19   886.4 1035.92   915.4 1041.89
#Mann= 3 , 0 , 0
       0      .1       0     454    .045       0     469      .1       0
Bank Sta=454,469
XS Rating Curve= 0 ,0
Exp/Cntr=0.3,0.1

Type RM Length L Ch R = 1 ,2279.3  ,297.906,302.554,318.773
XS GIS Cut Line= 3
     1767669.816      370395.696     1767313.566      370661.163
       1766859.1       370997.54
#Sta/Elev= 30
       0 1079.21      29 1069.19    57.9 1060.77    77.3 1056.92   173.8 1026.67
   241.5 1009.19   260.8 1006.66     338  989.58   405.6  967.01   434.6  954.42
   474.4  949.92   483.3  949.79   489.4  950.91   541.8   959.4   561.3  967.29
   580.8  977.55   600.3  983.92   658.7 1019.39   678.2 1028.14   697.7  1041.6
     727 1053.01   775.7 1075.28   785.5 1077.34     844 1103.91   863.5 1108.76
   902.5 1130.73   912.2 1134.37   941.5 1137.59   970.7 1145.36  1009.7 1151.12
#Mann= 3 , 0 , 0
       0      .1       0   474.4    .045       0   489.4      .1       0
Bank Sta=474.4,489.4
XS Rating Curve= 0 ,0
Exp/Cntr=0.3,0.1

Type RM Length L Ch R = 1 ,1976.8  ,391.227,400,396.937
XS GIS Cut Line= 3
     1767612.025      370306.328      1767163.03      370446.658
     1766701.984       370400.54
#Sta/Elev= 30
       0 1070.53   127.4 1031.99     147 1024.74   156.8 1023.23   186.2 1011.68
   264.6  986.46   313.6  965.97   333.2  962.18   382.2  957.32   431.2  945.66
   460.6  943.57   462.9  943.73   470.4  944.23   477.9  946.86   499.4  960.53
   528.3  973.03   557.3  983.63   576.6  988.38   605.6   998.3   624.9 1008.71
   634.5 1010.64   682.8 1034.24   692.4 1036.28   711.7 1045.52   721.4  1047.8
   740.7 1056.09   808.3 1075.53   846.9 1082.89   914.5 1104.79   933.8 1112.88
#Mann= 3 , 0 , 0
       0      .1       0   462.9    .045       0   477.9      .1       0
Bank Sta=462.9,477.9
XS Rating Curve= 0 ,0
Exp/Cntr=0.3,0.1

Type RM Length L Ch R = 1 ,1576.8  ,401.6,400,390.14
XS GIS Cut Line= 3
     1767598.651      370034.541     1767143.872      370050.376
     1766689.397      370072.126
#Sta/Elev= 30
       0  1076.6    19.4 1068.57    77.5 1048.65    87.1 1047.31   164.6 1018.94
   203.3  1007.9   222.7  999.62   329.2  973.62   358.2  962.14   406.6  939.55
   445.4  937.64   447.6  937.73   462.6  939.69   484.1  945.08   513.1  958.21
   532.5  971.61   542.2  975.07   561.5  987.84   571.2  991.02   590.6 1002.18
   600.3 1004.58   619.6 1016.15   629.3 1018.33   648.7 1030.73   658.4 1034.01
   677.7 1045.36   687.4 1047.51   706.8 1059.83   735.8 1073.94   910.1 1143.25
#Mann= 3 , 0 , 0
       0      .1       0   447.6    .045       0   462.6      .1       0
Bank Sta=447.6,462.6
XS Rating Curve= 0 ,0
Exp/Cntr=0.3,0.1

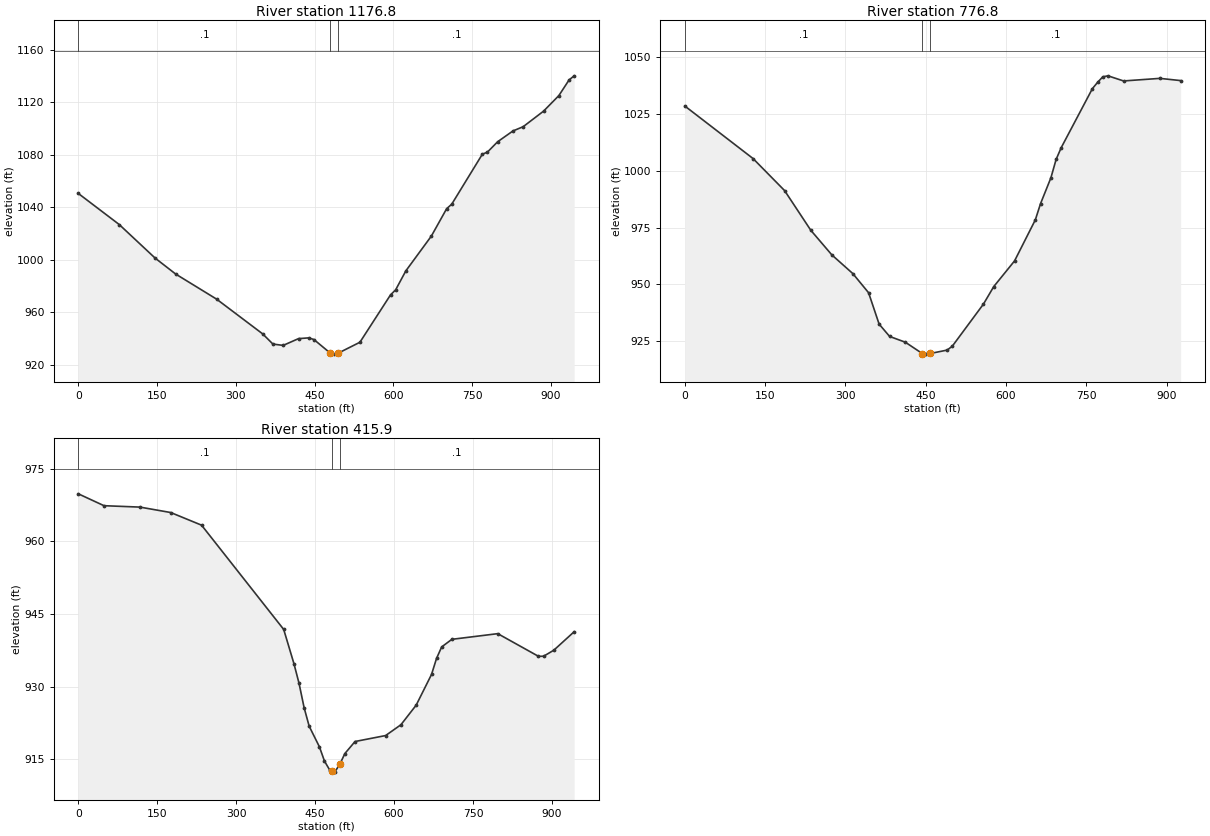
Type RM Length L Ch R = 1 ,1176.8  ,399.606,400,411.129
XS GIS Cut Line= 3
     1767553.341      369597.214      1767071.66       369674.24
     1766668.062      369888.056
#Sta/Elev= 30
       0  1050.5      78 1026.83   146.3 1001.32   185.4   989.2   263.4   970.1
   351.2  943.65   370.7   935.9   390.2  934.91   419.5  940.06     439  940.63
   448.8  939.36   480.3  928.92   487.8  928.26   495.3  929.06   536.4   937.3
   594.7  973.34   604.4  977.14   623.8  991.56   672.4 1018.03   701.6 1038.91
   711.3 1042.34   769.6 1080.36   779.3 1081.97   798.8 1089.86   827.9 1098.06
   847.4  1101.3   886.2 1113.12   915.4 1124.98   934.8 1136.87   944.5    1140
#Mann= 3 , 0 , 0
       0      .1       0   480.3    .045       0   495.3      .1       0
Bank Sta=480.3,495.3
XS Rating Curve= 0 ,0
Exp/Cntr=0.3,0.1

Type RM Length L Ch R = 1 ,776.8   ,364.027,360.899,355.592
XS GIS Cut Line= 3
     1767578.537       369262.35     1767129.468      369306.579
      1766654.54      369307.314
#Sta/Elev= 30
       0 1028.39   127.5 1005.31   186.4  991.24   235.4   973.8   274.7  962.99
   313.9  954.78   343.3  946.38     363  932.59   382.6  927.18     412  924.64
   443.7  919.66   451.2  919.41   458.7   919.7     490  921.18   499.7   922.9
   557.9   941.4   577.2   949.1     616  960.36   654.8  978.39   664.5  985.49
   683.9  996.86   693.6 1004.92   703.2 1010.12   761.4 1036.02   771.1 1038.78
   780.8  1041.2   790.5 1041.64   819.6 1039.39   887.4 1040.52   926.2 1039.55
#Mann= 3 , 0 , 0
       0      .1       0   443.7    .045       0   458.7      .1       0
Bank Sta=443.7,458.7
XS Rating Curve= 0 ,0
Exp/Cntr=0.3,0.1

Type RM Length L Ch R = 1 ,415.9   ,421.023,415.887,410.749
XS GIS Cut Line= 3
     1767560.481      368914.869     1767170.428      368929.183
     1766633.657      369058.008
#Sta/Elev= 30
       0  969.79    48.8  967.34   117.1  967.05   175.6  965.93   234.2  963.32
   390.3   941.8   409.7  934.76   419.4   930.7   429.1  925.65   438.7  921.83
   458.1  917.59   467.8  914.63   477.5  912.82   482.2  912.59   487.2  912.35
   497.2  914.02   506.5  916.18   525.9  918.67     584   919.9   613.1  922.13
   642.1  926.18   671.2   932.5   680.8  935.83   690.5  938.19   709.9  939.76
   797.1  940.93   874.5  936.25   884.2  936.27   903.6  937.51   942.3  941.33
#Mann= 3 , 0 , 0
       0      .1       0   482.2    .045       0   497.2      .1       0
Bank Sta=482.2,497.2
XS Rating Curve= 0 ,0
Exp/Cntr=0.3,0.1

Chan Stop Cuts=-1
Use User Specified Reach Order=0